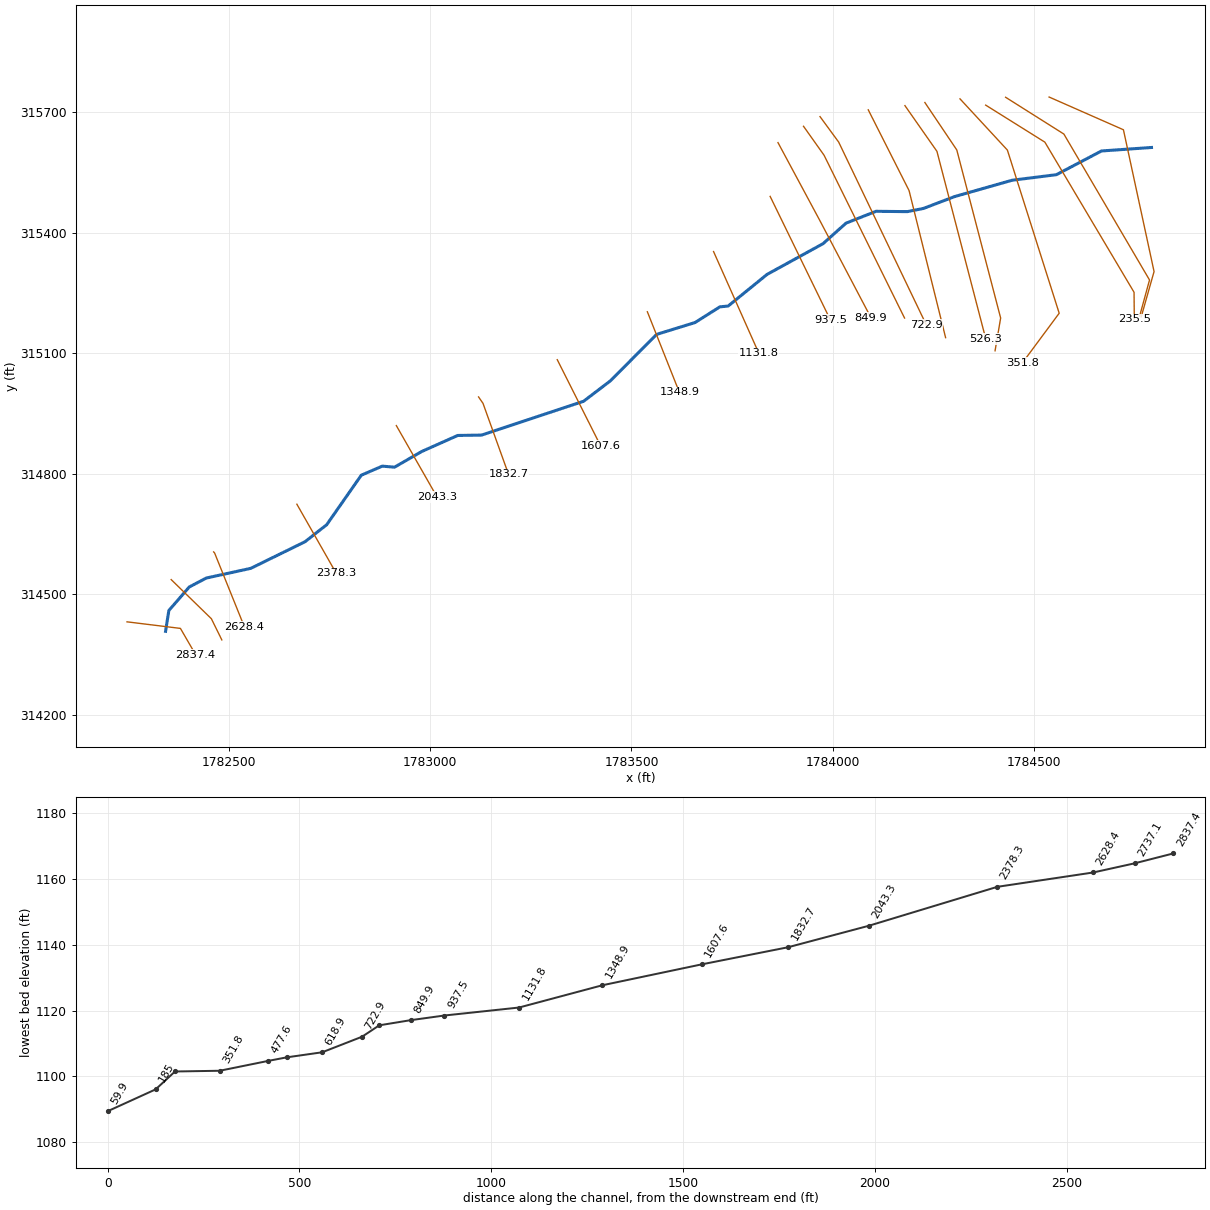
--- JASWORKBR.prj (project) ---

Proj Title=JASWORKBR
Current Plan=p01
Default Exp/Contr=0,0
English Units
Geom File=g01
Flow File=f01
Plan File=p01
BEGIN DESCRIPTION:
END DESCRIPTION:
DSS Export Rating Curves= 0
DSS Export Rating Curve Sorted= 0
DSS Export Volume Flow Curves= 0
DXF OffsetX= 0
DXF OffsetY= 0
DXF ScaleX= 0
DXF ScaleY= 0

--- JASWORKBR.p01 (plan) ---

Plan Title=Floodplain
Program Version=4.00
Geom File=g01
Flow File=f01
K Sum by GR=0
Std Step Tol=0.01
Critical Tol=0.01
Num of Std Step Trials=20
Max Error Tol=0.3
Flow Tol Ratio=0.001
Split Flow NTrial=30
Split Flow Tol=0.02
Split Flow Ratio=0.02
Log Output Level=0
Friction Slope Method=1
Unsteady Friction Slope Method=2
Unsteady Bridges Friction Slope Method=1
Global Log Level=0
CheckData=False
Run HTab=0
Run UNet=0
Run PostProcess=0
UNET Theta=0
UNET Theta Warmup=0
UNET ZTol=0
UNET ZSATol=0
UNET MxIter=0
UNET MaxInSteps=0
UNET DtIC=0
UNET DtMin=0
UNET MaxCRTS=0
UNET WFStab=0
UNET SFStab=0
UNET WFX=0
UNET SFX=0
UNET DSS MLevel=0
UNET DZMax Abort=0
UNET Convert EG Bridges=0
UNET Use Existing IB Tables=0
UNET Froude Limit=0
UNET Froude Power=0
Write IC File=0
Echo Input=False
Echo Output=False
Write Detailed=0

--- JASWORKBR.f01 (steady flow) ---

Flow Title=NFF Regression Equation
Program Version=4.10
Number of Profiles= 1
Profile Names=P100yr
River Rch & RM=JASWORKBR,Main            ,2837.4
882.5891
River Rch & RM=JASWORKBR,Main            ,2628.4
1094.609
River Rch & RM=JASWORKBR,Main            ,618.9
1153.485
River Rch & RM=JASWORKBR,Main            ,351.8
1155.567
Boundary for River Rch & Prof#=JASWORKBR,Main            , 1
Up Type= 0
Dn Type= 3
Dn Slope=0.05823
DSS Import GetInterval= 0
DSS Import GetPeak= 0
DSS Import FillOption= 0

--- JASWORKBR.g01 (geometry) ---

Geom Title=USGS 10m DEM
Program Version=5.03

River Reach=JASWORKBR       ,Main
Reach XY= 30
     1782342.756      314408.103     1782350.909      314459.981
     1782401.676       314518.53      1782443.92      314540.764
     1782554.348      314564.851     1782689.154      314631.126
     1782742.973      314673.488     1782828.911      314796.751
     1782880.994      314819.321     1782911.376      314816.717
     1782979.085      314855.779     1783068.494       314895.71
     1783127.522      314896.578     1783380.995      314980.779
     1783447.834      315031.821     1783562.418      315147.272
     1783657.904      315176.786     1783719.536      315215.849
     1783740.192      315217.894     1783836.723      315296.578
     1783975.612      315372.966     1784032.904      315424.182
     1784107.557      315453.696     1784184.814      315452.828
     1784224.744       315460.64     1784302.001      315490.154
      1784445.23      315530.953     1784555.473      315544.842
     1784667.453       315603.87     1784791.585       315612.55

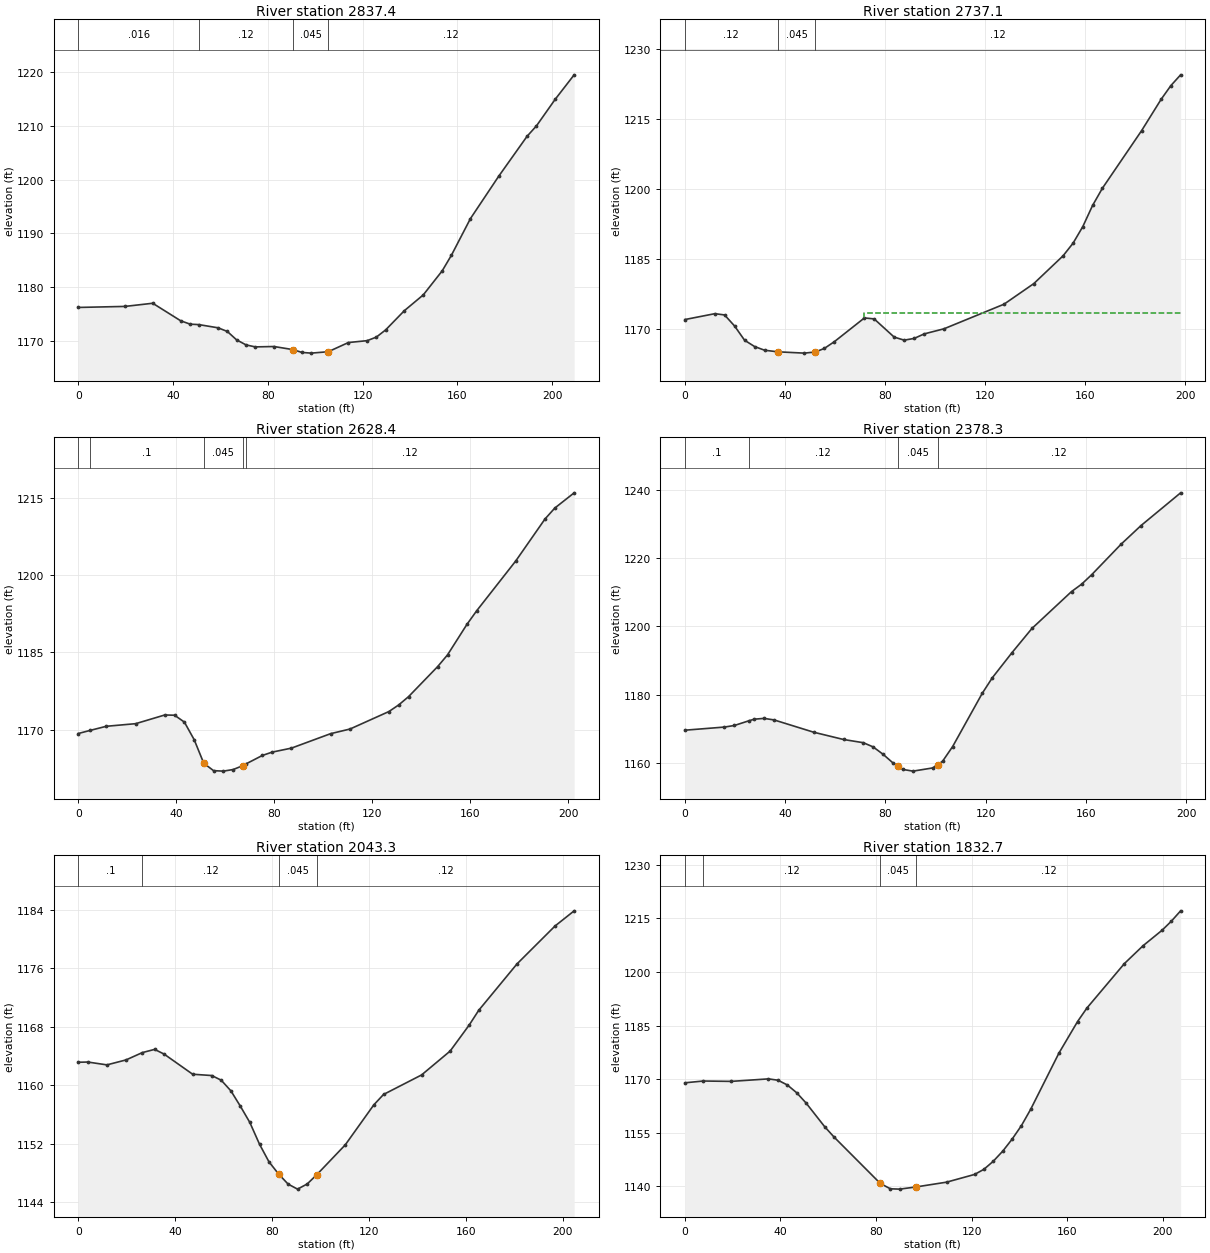
Type RM Length L Ch R = 1 ,2837.4  ,115.2,100.4,85.6
XS GIS Cut Line= 3
     1782247.017      314431.737     1782379.683      314415.388
      1782417.54      314349.958
#Sta/Elev= 30
       0 1176.24    19.7 1176.43    31.4 1177.02    43.2 1173.76    47.2 1173.13
   50.881173.045      59 1172.45    62.9 1171.77    66.8 1170.21    70.8 1169.27
    74.7  1168.9    82.6 1168.97    90.5  1168.4    94.4 1167.87    98.3 1167.74
   105.5    1168     114 1169.71   121.9 1170.06   125.8 1170.72   129.7 1172.05
   137.6 1175.63   145.6 1178.57   153.6 1183.05   157.5 1185.96   165.5 1192.76
   177.4 1200.62   189.4 1208.07   193.4 1210.03   201.3 1214.97   209.3 1219.52
#Mann= 4 ,-1 , 0
       0    .016       0   50.88     .12       0    90.5    .045       0
   105.5     .12       0
Bank Sta=90.5,105.5
XS Rating Curve= 0 ,0
Exp/Cntr=0.3,0.1

Type RM Length L Ch R = 1 ,2737.1  ,118,108.6,99.2
XS GIS Cut Line= 3
     1782356.714       314536.91     1782456.541      314439.459
     1782482.452       314386.79
#Sta/Elev= 30
       0 1171.94      12  1173.2    15.9 1172.93    19.9 1170.56    23.9 1167.51
    27.9 1166.16    31.9 1165.37    37.2 1165.03    47.8 1164.75    52.2    1165
    55.8 1165.76    59.8 1167.21    71.8 1172.29    75.7 1172.08    83.7 1168.18
    87.7 1167.53    91.7  1167.9    95.7 1168.87   103.6 1169.96   127.6 1175.23
   139.5 1179.64   151.2 1185.59   155.2  1188.3   159.1 1191.86     163 1196.38
   166.9 1200.05   182.6 1212.41   190.4 1219.12   194.3 1222.06   198.2 1224.37
#Mann= 3 ,-1 , 0
       0     .12       0    37.2    .045       0    52.2     .12       0
#XS Ineff= 2 , 0
                           71.83         1173.36
Permanent Ineff=
       F       F
Bank Sta=37.2,52.2
XS Rating Curve= 0 ,0
Exp/Cntr=0.3,0.1

Type RM Length L Ch R = 1 ,2628.4  ,247,250.1,253.3
XS GIS Cut Line= 3
     1782462.132      314605.846     1782464.504      314603.284
     1782538.739      314418.728
#Sta/Elev= 30
       0 1169.26    4.871169.869    11.4 1170.66    23.4 1171.17    35.3 1172.86
    39.3 1172.81    43.3 1171.47    47.3 1168.05    51.2 1163.48    55.2 1162.04
    59.2 1161.95    63.2 1162.26    67.2 1163.02   68.55 1163.38    75.1 1164.99
    79.1 1165.64      87 1166.42     103 1169.23   110.9 1170.13   126.8 1173.53
   130.8 1174.82   134.8 1176.42   146.7 1182.27   150.7 1184.53   158.6 1190.44
   162.6  1193.1   178.6 1202.81   190.5 1210.94   194.5 1213.06   202.4 1216.02
#Mann= 5 ,-1 , 0
       0     .05       0    4.87      .1       0    51.2    .045       0
    67.2      .1       0   68.55     .12       0
Bank Sta=51.2,67.2
XS Rating Curve= 0 ,0
Exp/Cntr=0.3,0.1

Type RM Length L Ch R = 1 ,2378.3  ,334.8,335,335.2
XS GIS Cut Line= 2
     1782668.896      314724.549     1782766.671      314552.671
#Sta/Elev= 30
       0 1169.57    15.8 1170.49    19.8 1170.96   25.491172.314    27.7  1172.8
    31.6 1173.03    35.6 1172.58    51.4 1168.98    63.3 1166.85    71.2 1165.91
    75.1 1164.68    79.1  1162.5      83 1159.99   84.951159.054      87 1158.07
      91 1157.59    98.9 1158.53  100.78 1159.48   102.8  1160.5   106.8 1164.79
   118.6 1180.37   122.6 1184.91   130.5 1192.31   138.4 1199.35   154.2 1210.16
   158.2 1212.31   162.2 1215.07     174 1224.06   181.9 1229.48   197.7 1239.07
#Mann= 4 ,-1 , 0
       0      .1       0   25.49     .12       0   84.95    .045       0
  100.78     .12       0
Bank Sta=84.95,100.78
XS Rating Curve= 0 ,0
Exp/Cntr=0.3,0.1

Type RM Length L Ch R = 1 ,2043.3  ,214.4,210.5,206.6
XS GIS Cut Line= 2
     1782915.899      314920.301      1783017.15      314742.428
#Sta/Elev= 30
       0 1163.13     3.9 1163.16    11.8 1162.77    19.7 1163.45   26.421164.453
    31.5 1164.89    35.4 1164.25    47.2 1161.49    55.1 1161.31      59 1160.67
      63 1159.21    66.9 1157.11    70.8 1154.89    74.8 1151.91    78.7  1149.5
    82.7 1147.82    86.6 1146.45    90.5 1145.76    94.5 1146.47    98.4 1147.72
   110.2 1151.82     122  1157.3     126 1158.72   141.7 1161.39   153.5 1164.66
   161.4 1168.24   165.3 1170.24   181.1 1176.59   196.8 1181.78   204.7 1183.86
#Mann= 4 ,-1 , 0
       0      .1       0   26.42     .12       0    82.7    .045       0
    98.4     .12       0
Bank Sta=82.7,98.4
XS Rating Curve= 0 ,0
Exp/Cntr=0.3,0.1

Type RM Length L Ch R = 1 ,1832.7  ,222.4,225.1,227.9
XS GIS Cut Line= 3
     1783120.155      314991.601     1783131.171       314975.68
      1783194.73      314798.702
#Sta/Elev= 30
       0    1169    7.74  1169.5    19.4  1169.4      35  1170.1      39 1169.72
    42.9 1168.39    46.8 1166.22    50.7 1163.37    58.5 1156.72    62.4 1153.84
    81.8 1140.82      86 1139.33    89.9 1139.24    96.8 1139.86   109.5 1141.19
   121.2 1143.35   125.1 1144.78     129 1147.02     133 1149.88   136.9 1153.22
   140.8 1157.01   144.7 1161.61   156.5 1177.32   164.3 1186.16   168.2 1189.93
   183.9 1202.39   191.7 1207.38   199.6 1211.68   203.5 1214.22   207.4 1217.14
#Mann= 4 ,-1 , 0
       0      .1       0    7.74     .12       0    81.8    .045       0
    96.8     .12       0
Bank Sta=81.8,96.8
XS Rating Curve= 0 ,0
Exp/Cntr=0.3,0.1

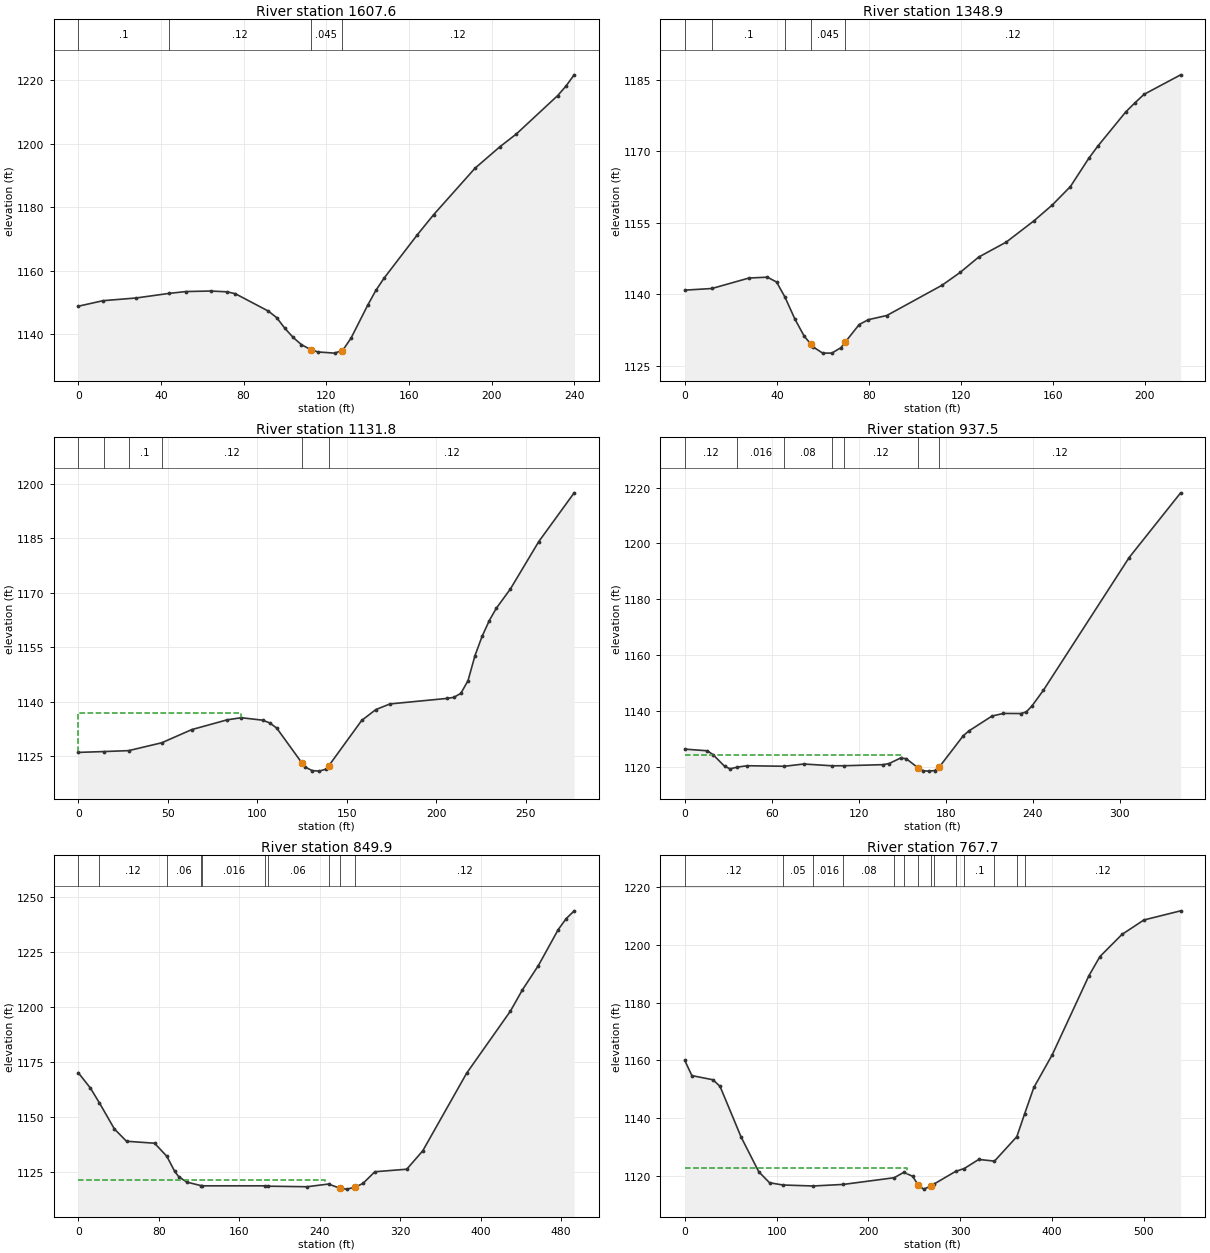
Type RM Length L Ch R = 1 ,1607.6  ,260.7,258.7,256.6
XS GIS Cut Line= 2
     1783315.638      315084.316      1783423.34       314869.84
#Sta/Elev= 30
       0 1148.82      12 1150.56      28 1151.41   43.991152.859      52 1153.43
      64  1153.6      72 1153.35      76 1152.75      92 1147.27      96 1145.22
     100 1141.84     104 1138.97     108 1136.71   112.4 1135.18     116 1134.41
     124 1134.04   127.4  1134.8     128 1134.94     132 1138.77     140 1149.05
     144 1153.78     148 1157.67     164 1171.24     172 1177.66     192 1192.27
     204 1199.01     212 1203.05     232 1215.14     236 1218.11     240 1221.69
#Mann= 4 ,-1 , 0
       0      .1       0   43.99     .12       0   112.4    .045       0
   127.4     .12       0
Bank Sta=112.4,127.4
XS Rating Curve= 0 ,0
Exp/Cntr=0.3,0.1

Type RM Length L Ch R = 1 ,1348.9  ,216.1,217.1,218.2
XS GIS Cut Line= 2
     1783539.436      315203.615      1783618.89      315003.253
#Sta/Elev= 30
       0 1140.89   11.771141.237    27.9 1143.43    35.9 1143.61    39.9 1142.59
   43.541139.423    47.9 1134.79    51.9 1131.25   54.731129.628    55.9 1128.96
    59.9 1127.71    63.9  1127.7    67.9 1128.86   69.721130.009    75.8 1133.69
    79.8 1134.71    87.8 1135.58   111.8 1141.92   119.7 1144.61   127.7 1147.81
   139.7 1150.95   151.7 1155.39   159.7 1158.72   167.6 1162.59   175.6 1168.52
   179.6 1171.11   191.6 1178.19   195.6 1180.11   199.6  1181.9   215.5 1185.99
#Mann= 5 ,-1 , 0
       0     .05       0   11.77      .1       0   43.54     .12       0
   54.73    .045       0   69.72     .12       0
Bank Sta=54.73,69.72
XS Rating Curve= 0 ,0
Exp/Cntr=0.3,0.1

Type RM Length L Ch R = 1 ,1131.8  ,193.3,194.3,194.9
XS GIS Cut Line= 2
     1783703.888      315353.408     1783816.405      315100.245
#Sta/Elev= 30
       0 1126.09   14.291126.324   28.111126.578   46.611128.739    63.3 1132.35
    83.1 1135.04      91 1135.63   102.9 1134.96   106.9 1134.21   110.8  1132.8
  125.111123.062   126.6  1122.1   130.6 1121.09   134.6 1120.94   138.5 1121.52
  139.861122.374   158.3 1134.88   166.2 1137.87   174.1 1139.42   205.8 1140.93
   209.8 1141.23   213.7 1142.34   217.7 1145.82   221.6 1152.72   225.6 1158.05
   229.6 1162.36   233.5 1165.73   241.4 1171.06   257.2 1184.05     277 1197.48
#Mann= 6 ,-1 , 0
       0    .016       0   14.29     .06       0   28.11      .1       0
   46.61     .12       0  125.11    .045       0  139.86     .12       0
#XS Ineff= 2 , 0
           91.02 1136.89
Permanent Ineff=
       F       F
Bank Sta=125.11,139.86
XS Rating Curve= 0 ,0
Exp/Cntr=0.3,0.1

Type RM Length L Ch R = 1 ,937.5   ,87.2,87.7,88.2
XS GIS Cut Line= 3
     1783844.411      315490.778      1783897.41      315381.848
     1783994.048      315183.226
#Sta/Elev= 30
       0 1126.39    15.6  1125.8    19.5  1124.4    27.4 1120.29    31.3 1119.33
   35.911119.929      43 1120.45   68.75 1120.26    82.1 1121.07   101.6 1120.43
  109.98 1120.45   136.9 1120.84   140.9 1121.23   148.8 1123.21   152.7 1122.99
   160.6 1119.81   164.5 1118.64   168.5 1118.52   172.4 1118.73   175.6 1120.03
   192.1  1131.2   196.1 1132.96   211.9 1138.23   219.8 1139.17   231.6 1139.13
   235.5 1139.68   239.5 1141.87   247.4  1147.5   306.5 1194.96     342 1218.11
#Mann= 7 ,-1 , 0
       0     .12       0   35.91    .016       0   68.75     .08       0
   101.6     .06       0  109.98     .12       0   160.6    .045       0
   175.6     .12       0
#XS Ineff= 2 , 0
           149.9 1124.32
Permanent Ineff=
       F       F
Bank Sta=160.6,175.6
XS Rating Curve= 0 ,0
Exp/Cntr=0.3,0.1

Type RM Length L Ch R = 1 ,849.9   ,82.5,82.2,81.8
XS GIS Cut Line= 3
     1783863.908      315624.684     1783967.568       315431.19
     1784094.664      315189.098
#Sta/Elev= 30
       0    1170      12 1163.04      211156.285    35.9 1144.42    47.9 1138.87
    75.8 1137.98   88.021132.002    95.8 1125.19    99.8 1122.76   107.8 1120.32
  121.531118.749  123.171118.614  185.711118.616  188.551118.449   227.4  1118.2
  248.711119.426   260.5 1117.44   267.1 1117.11   275.5 1118.05   282.9 1119.69
   294.8 1125.01   326.5 1126.16   342.4 1134.54     386 1169.79   429.5    1198
   441.4 1207.63   457.3  1218.7   477.1  1235.1     485 1240.05   492.9 1243.59
#Mann= 10 ,-1 , 0
       0    .016       0      21     .12       0   88.02     .06       0
  121.53     .05       0  123.17    .016       0  185.71     .08       0
  188.55     .06       0  248.71     .12       0   260.5    .045       0
   275.5     .12       0
#XS Ineff= 2 , 0
          245.61 1121.28
Permanent Ineff=
       F       F
Bank Sta=260.5,275.5
XS Rating Curve= 0 ,0
Exp/Cntr=0.3,0.1

Type RM Length L Ch R = 1 ,767.7   ,45.1,44.8,44.6
XS GIS Cut Line= 3
      1783927.31      315665.282     1783978.349      315593.243
     1784178.215      315188.013
#Sta/Elev= 30
       0    1160     7.7 1154.77    30.7 1153.33    38.4 1151.04    61.4  1133.5
    80.6 1121.53    92.3 1117.75  106.811116.969  139.751116.625  172.681117.168
  228.151119.482  238.551121.354   248.2 1119.97  254.39 1116.87   260.2 1115.54
   268.2 1116.59  271.481117.303  294.911121.653  304.421122.664   320.2  1125.8
  337.35 1125.22  361.681133.679  370.291141.664   380.2 1150.66   400.2 1161.94
   440.2 1189.29   452.2 1195.91   476.2 1203.55   500.1 1208.55   540.1 1211.71
#Mann= 14 ,-1 , 0
       0     .12       0  106.81     .05       0  139.75    .016       0
  172.68     .08       0  228.15    .016       0  238.55     .06       0
  254.39    .045       0   268.2     .06       0  271.48      .1       0
  294.91    .016       0  304.42      .1       0  337.35     .12       0
  361.68      .1       0  370.29     .12       0
#XS Ineff= 2 , 0
          242.11 1122.91
Permanent Ineff=
       F       F
Bank Sta=254.39,268.2
XS Rating Curve= 0 ,0
Exp/Cntr=0.3,0.1

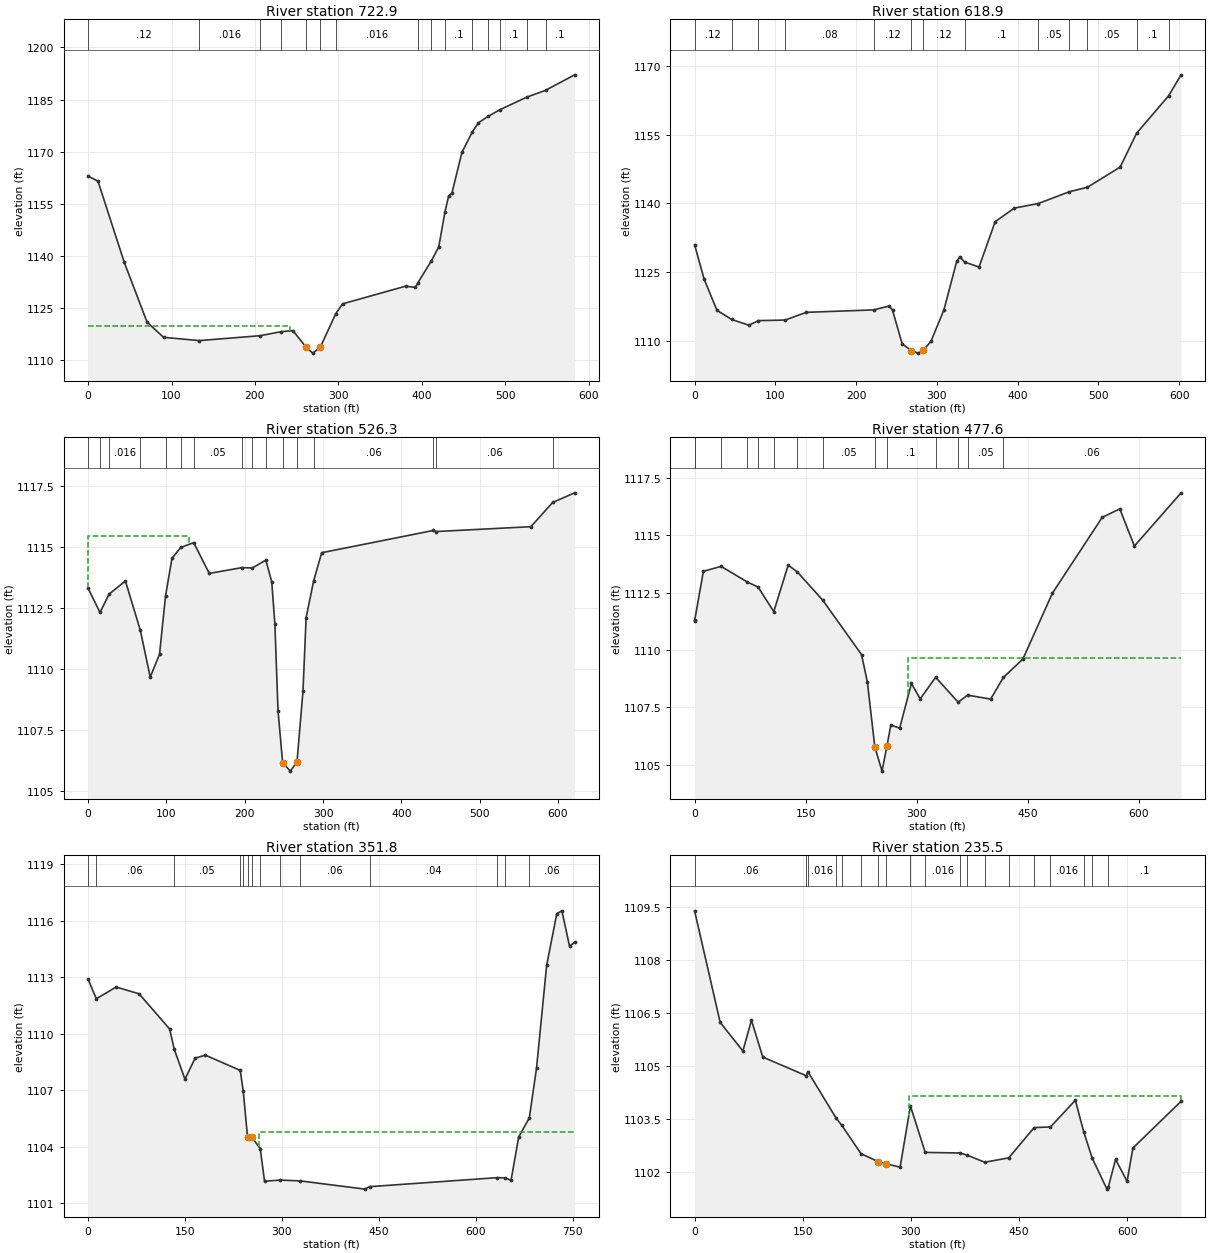
Type RM Length L Ch R = 1 ,722.9   ,108.6,104,99.3
XS GIS Cut Line= 3
     1783968.283      315689.378     1784014.651      315625.941
     1784232.468      315170.652
#Sta/Elev= 30
       0 1162.96    11.8 1161.53    43.2 1138.28    70.7 1120.98    90.5 1116.62
  133.241115.686  206.251117.091  231.47 1118.25   245.5 1118.55   261.4 1113.76
   269.3 1112.08  278.19  1113.7  296.961123.436   305.1 1126.25   380.6 1131.33
   392.5 1130.96  395.191132.231  411.551138.605   420.4 1142.64  427.931152.794
   432.3  1157.3   436.2  1158.1   448.2 1169.83  460.681175.706     468 1178.33
  479.981180.198  493.421182.044  526.161185.707  548.421187.637   583.3  1192.1
#Mann= 15 ,-1 , 0
       0     .12       0  133.24    .016       0  206.25     .08       0
  231.47    .016       0   261.4    .045       0  278.19      .1       0
  296.96    .016       0  395.19      .1       0  411.55     .05       0
  427.93      .1       0  460.68     .12       0  479.98     .05       0
  493.42      .1       0  526.16     .12       0  548.42      .1       0
#XS Ineff= 2 , 0
          242.11 1119.93
Permanent Ineff=
       F       F
Bank Sta=261.4,278.19
XS Rating Curve= 0 ,0
Exp/Cntr=0.3,0.1

Type RM Length L Ch R = 1 ,618.9   ,92.3,92.6,92.8
XS GIS Cut Line= 3
     1784088.075      315706.305     1784189.498      315505.214
     1784280.211      315139.185
#Sta/Elev= 30
       0    1131    11.8  1123.5    27.7  1116.7      461114.692    67.2 1113.44
   79.081114.443  112.161114.564   138.3 1116.25  221.671116.781   241.1 1117.63
   245.1 1116.69     257 1109.38   268.3 1107.91   276.8 1107.35   283.3 1107.99
   292.7 1109.95   308.6 1116.75   324.5 1127.35   328.4  1128.4  334.241127.214
   352.2 1126.14   372.1 1136.03   395.9 1138.99  425.531139.987  464.091142.568
  486.39 1143.54   526.9 1147.95  547.251155.341  586.85  1163.5   602.3 1168.07
#Mann= 13 ,-1 , 0
       0     .12       0      46     .05       0   79.08    .016       0
  112.16     .08       0  221.67     .12       0   268.3    .045       0
   283.3     .12       0  334.24      .1       0  425.53     .05       0
  464.09      .1       0  486.39     .05       0  547.25      .1       0
  586.85     .05       0
Bank Sta=268.3,283.3
XS Rating Curve= 0 ,0
Exp/Cntr=0.3,0.1

Type RM Length L Ch R = 1 ,526.3   ,48.7,48.7,48.8
XS GIS Cut Line= 3
     1784179.221      315716.722     1784258.688      315602.937
     1784380.038       315135.93
#Sta/Elev= 30
       0 1113.32   15.171112.325   26.781113.078    47.6 1113.62   66.751111.587
    79.3 1109.67    91.2 1110.61   98.841112.999   107.1 1114.55  118.331114.997
  134.861115.194   154.7 1113.93   196.51114.168  209.651114.154  227.021114.476
   234.5 1113.58   238.5 1111.86   242.5  1108.3  248.43 1106.15   258.4 1105.81
  266.78  1106.2   274.4 1109.09   278.4 1112.11  288.051113.632   298.3 1114.78
  440.641115.693  444.49 1115.65   565.5 1115.85  593.231116.845   621.3 1117.24
#Mann= 16 ,-1 , 0
       0     .12       0   15.17     .05       0   26.78    .016       0
   66.75     .06       0   98.84     .08       0  118.33     .06       0
  134.86     .05       0   196.5     .06       0  209.65     .05       0
  227.02     .12       0  248.43    .045       0  266.78     .12       0
  288.05     .06       0  440.64     .05       0  444.49     .06       0
  593.23     .12       0
#XS Ineff= 2 , 0
          129.31 1115.45
Permanent Ineff=
       F       F
Bank Sta=248.43,266.78
XS Rating Curve= 0 ,0
Exp/Cntr=0.3,0.1

Type RM Length L Ch R = 1 ,477.6   ,124.5,125.8,127
XS GIS Cut Line= 4
       1784228.7      315724.534     1784307.994      315606.409
      1784416.93      315188.013     1784403.067      315106.431
#Sta/Elev= 30
       0 1111.28     .281111.316    11.9 1113.43   35.861113.644   71.431112.961
   85.791112.743  107.011111.673   126.5  1113.7  138.781113.403  173.061112.175
   225.6  1109.8   233.5  1108.6  243.52 1105.78   253.3 1104.72  259.85  1105.8
   265.2 1106.73   277.1 1106.59     293 1108.54   304.9 1107.87  325.67 1108.81
  356.191107.726  368.951108.031   400.1 1107.86  417.231108.802   443.7 1109.61
   483.4 1112.47   550.8 1115.78   574.6 1116.15   594.3 1114.53   657.4 1116.85
#Mann= 14 ,-1 , 0
       0     .05       0     .28    .016       0   35.86     .08       0
   71.43     .06       0   85.79     .06       0  107.01     .05       0
  138.78     .06       0  173.06     .05       0  243.52    .045       0
  259.85      .1       0  325.67     .12       0  356.19     .06       0
  368.95     .05       0  417.23     .06       0
#XS Ineff= 2 , 0
                          288.96         1109.65
Permanent Ineff=
       F       F
Bank Sta=243.52,259.85
XS Rating Curve= 0 ,0
Exp/Cntr=0.3,0.1

Type RM Length L Ch R = 1 ,351.8   ,111.2,116.4,121.5
XS GIS Cut Line= 4
      1784315.94      315733.649     1784433.639      315606.126
     1784562.329      315199.949     1784471.096      315076.541
#Sta/Elev= 30
       0 1112.89   12.731111.856    43.4 1112.48    78.9 1112.12   126.2 1110.25
  133.321109.176   149.9 1107.58   165.6  1108.7   181.5 1108.86  235.49 1108.05
  240.051106.969  246.82  1104.5   253.2 1104.51  266.471103.893   273.1 1102.16
  297.451102.221  328.441102.177   428.4 1101.74   435.6 1101.87  633.27 1102.35
  645.45 1102.34   654.7 1102.21   666.5 1104.51  682.961105.523   694.1 1108.16
   709.8 1113.63   725.5 1116.38   733.4 1116.53   745.2 1114.65   753.1 1114.85
#Mann= 14 ,-1 , 0
       0    .016       0   12.73     .06       0  133.32     .05       0
  235.49      .1       0  240.05     .05       0  246.82    .045       0
   253.2     .05       0  266.47      .1       0  297.45     .05       0
  328.44     .06       0   435.6     .04       0  633.27     .06       0
  645.45     .05       0  682.96     .06       0
#XS Ineff= 2 , 0
                          264.19          1104.8
Permanent Ineff=
       F       F
Bank Sta=246.82,253.2
XS Rating Curve= 0 ,0
Exp/Cntr=0.3,0.1

Type RM Length L Ch R = 1 ,235.5   ,50.7,50.5,50.4
XS GIS Cut Line= 4
     1784379.742      315718.024     1784526.744      315625.854
      1784748.28      315252.135     1784748.877      315185.164
#Sta/Elev= 30
       0 1109.38    35.5 1106.23      67 1105.42    78.9 1106.29    94.6 1105.25
  155.021104.722  157.061104.842  196.431103.522  204.091103.326  230.761102.523
   254.2  1102.3   265.2 1102.24   285.1 1102.14  299.441103.868  319.931102.557
  368.111102.541  377.851102.482  402.45 1102.28  435.761102.402  471.121103.259
  493.681103.275   528.2 1104.03   539.8 1103.14   551.61102.393   572.1 1101.52
  574.131101.591     584 1102.36     600 1101.74     608 1102.68   674.9    1104
#Mann= 19 ,-1 , 0
       0     .06       0  155.02     .05       0  157.06    .016       0
  196.43     .05       0  204.09    .016       0  230.76     .05       0
   254.2    .045       0   265.2    .016       0  299.44     .05       0
  319.93    .016       0  368.11     .05       0  377.85    .016       0
  402.45     .05       0  435.76    .016       0  471.12     .05       0
  493.68    .016       0   539.8     .05       0   551.6    .016       0
  574.13      .1       0
#XS Ineff= 2 , 0
                           296.9         1104.16
Permanent Ineff=
       F       F
Bank Sta=254.2,265.2
XS Rating Curve= 0 ,0
Exp/Cntr=0.3,0.1

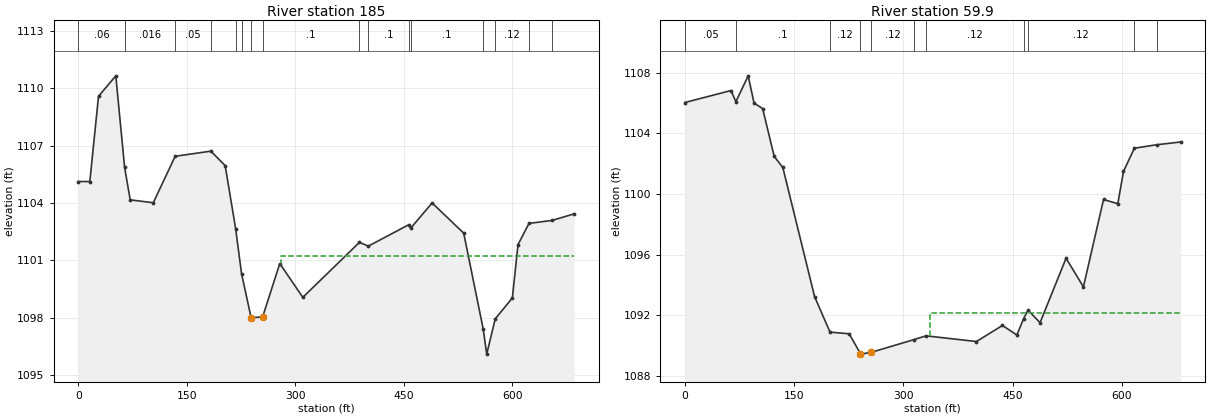
Type RM Length L Ch R = 1 ,185     ,132.2,125.1,117.9
XS GIS Cut Line= 4
     1784429.221      315737.555     1784573.966      315645.993
     1784786.706      315282.686     1784762.156      315192.838
#Sta/Elev= 30
       0 1105.12    15.9 1105.12    27.9 1109.58    51.8 1110.65   63.961105.866
    71.7 1104.16   103.6 1104.01  133.861106.441  183.231106.709     203 1105.95
  217.46 1102.65  225.591100.307   238.8    1098   254.7 1098.03   278.5 1100.83
   310.3 1099.06   388.61101.938  400.931101.741  457.061102.866  459.381102.675
     489    1104   532.7 1102.42  559.751097.388   564.5 1096.09  576.281097.934
     600 1099.03   607.8 1101.82  622.98 1102.93  655.031103.086   685.4 1103.43
#Mann= 16 ,-1 , 0
       0     .06       0   63.96    .016       0  133.86     .05       0
  183.23      .1       0  217.46    .016       0  225.59      .1       0
   238.8    .045       0   254.7      .1       0   388.6    .016       0
  400.93      .1       0  457.06    .016       0  459.38      .1       0
  559.75    .016       0  576.28     .12       0  622.98    .016       0
  655.03      .1       0
#XS Ineff= 2 , 0
                          280.29         1101.24
Permanent Ineff=
       F       F
Bank Sta=238.8,254.7
XS Rating Curve= 0 ,0
Exp/Cntr=0.3,0.1

Type RM Length L Ch R = 1 ,59.9    ,64.3,59.9,55.6
XS GIS Cut Line= 4
     1784537.268      315738.156     1784721.883       315656.67
     1784797.982      315303.722     1784765.975      315190.581
#Sta/Elev= 30
       0 1106.03    63.3 1106.82   70.121106.088      87 1107.79      95    1106
   106.8 1105.63   122.7 1102.48   134.5 1101.75   178.1 1093.24  199.26  1090.9
   225.6 1090.79   240.9 1089.49   241.5 1089.45   255.9 1089.57  313.931090.398
  330.891090.655   400.2 1090.28   435.9 1091.34   455.7 1090.71  465.011091.795
     4711092.347   487.5 1091.52   523.2 1095.77     547 1093.88   574.6 1099.64
   594.2 1099.36     602 1101.49  616.93 1103.02  647.631103.248   680.4 1103.43
#Mann= 11 ,-1 , 0
       0     .05       0   70.12      .1       0  199.26     .12       0
   240.9    .045       0   255.9     .12       0  313.93      .1       0
  330.89     .12       0  465.01      .1       0     471     .12       0
  616.93    .016       0  647.63      .1       0
#XS Ineff= 2 , 0
                          336.64         1092.14
Permanent Ineff=
       F       F
Bank Sta=240.9,255.9
XS Rating Curve= 0 ,0
Exp/Cntr=0.3,0.1
LCMann Table=0

Chan Stop Cuts=-1
Use User Specified Reach Order=0
Composite Channel Slope=5